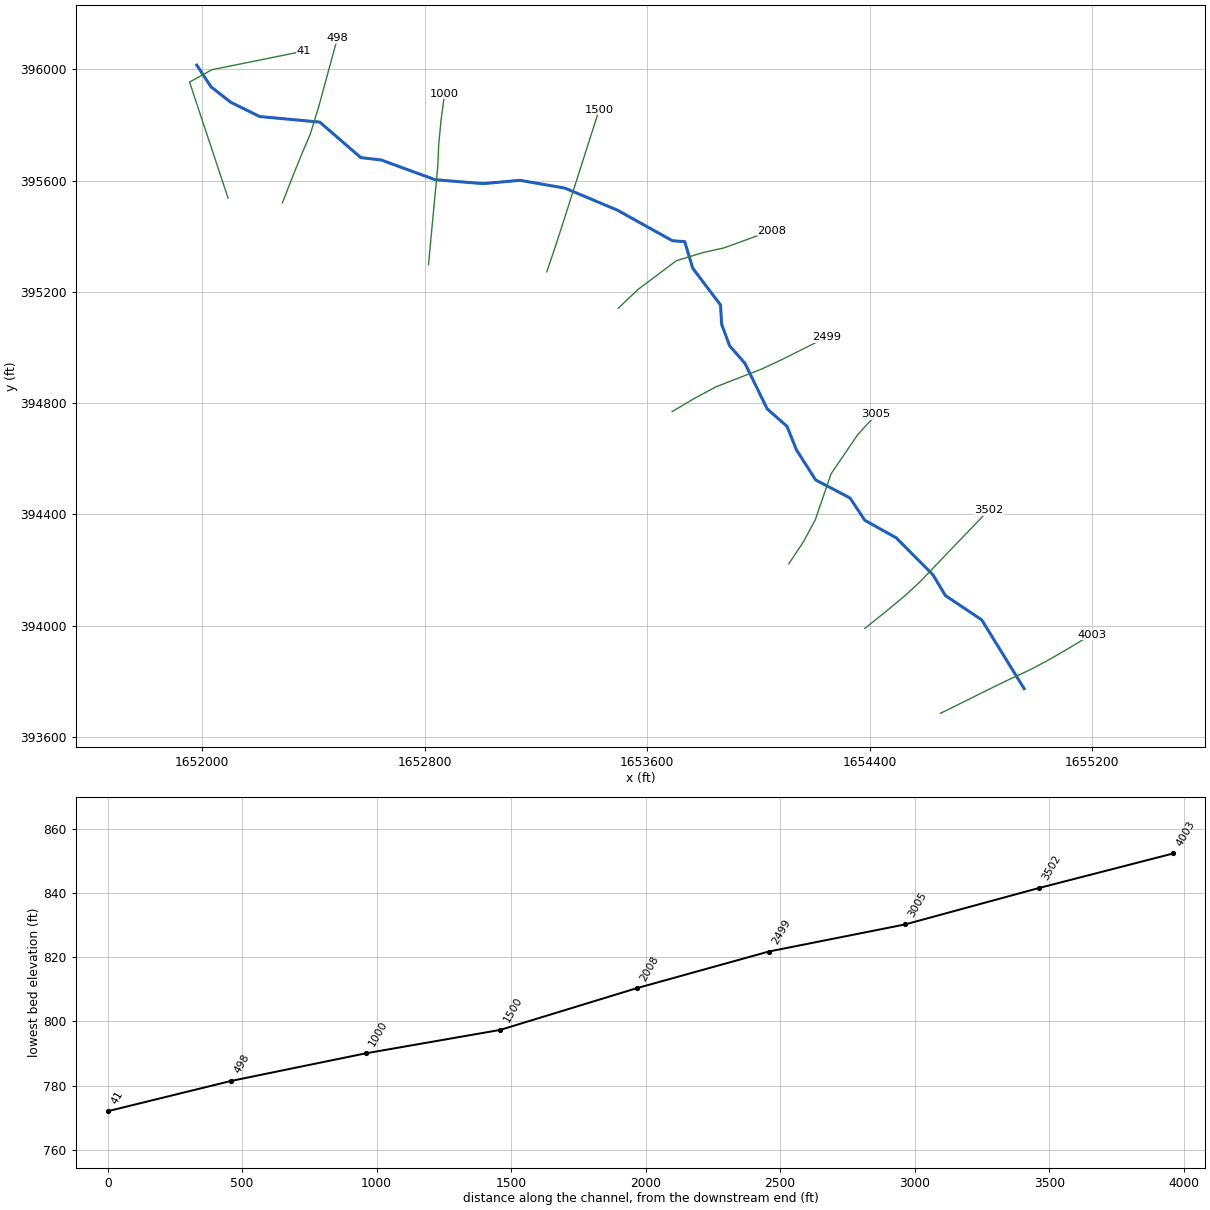
--- SHEEPRN.prj (project) ---

Proj Title=SHEEPRN
Current Plan=p01
Default Exp/Contr=0,0
English Units
Geom File=g01
Flow File=f01
Plan File=p01
BEGIN DESCRIPTION:
END DESCRIPTION:
DSS Export Rating Curves= 0
DSS Export Rating Curve Sorted= 0
DSS Export Volume Flow Curves= 0
DXF OffsetX= 0
DXF OffsetY= 0
DXF ScaleX= 0
DXF ScaleY= 0

--- SHEEPRN.p01 (plan) ---

Plan Title=Floodplain
Program Version=4.00
Geom File=g01
Flow File=f01
K Sum by GR=0
Std Step Tol=0.01
Critical Tol=0.01
Num of Std Step Trials=20
Max Error Tol=0.3
Flow Tol Ratio=0.001
Split Flow NTrial=30
Split Flow Tol=0.02
Split Flow Ratio=0.02
Log Output Level=0
Friction Slope Method=1
Unsteady Friction Slope Method=2
Unsteady Bridges Friction Slope Method=1
Global Log Level=0
CheckData=False
Run HTab=0
Run UNet=0
Run PostProcess=0
UNET Theta=0
UNET Theta Warmup=0
UNET ZTol=0
UNET ZSATol=0
UNET MxIter=0
UNET MaxInSteps=0
UNET DtIC=0
UNET DtMin=0
UNET MaxCRTS=0
UNET WFStab=0
UNET SFStab=0
UNET WFX=0
UNET SFX=0
UNET DSS MLevel=0
UNET DZMax Abort=0
UNET Convert EG Bridges=0
UNET Use Existing IB Tables=0
UNET Froude Limit=0
UNET Froude Power=0
Write IC File=0
Echo Input=False
Echo Output=False
Write Detailed=0

--- SHEEPRN.f01 (steady flow) ---

Flow Title=Flow
Program Version=6.31
Number of Profiles= 1
Profile Names=F01pct
River Rch & RM=SHEEPRN,Main            ,4003
     579
River Rch & RM=SHEEPRN,Main            ,2499
     670
Boundary for River Rch & Prof#=SHEEPRN,Main            , 1
Up Type= 0
Dn Type= 3
Dn Slope=0.01641
DSS Import GetInterval= 0
DSS Import GetPeak= 0
DSS Import FillOption= 0

--- SHEEPRN.g01 (geometry) ---

Geom Title=Geometry
Program Version=6.31

River Reach=SHEEPRN         ,Main
Reach XY= 30
      1654955.35      393773.478     1654802.723      394020.934
     1654672.163      394108.246      1654627.42      394182.891
     1654495.407       394315.79     1654382.664      394378.696
     1654329.504      394458.879     1654205.908      394523.778
       1654136.8      394631.869      1654102.91      394716.482
     1654031.809      394779.166     1653951.627      394942.854
     1653896.473      395006.203       1653867.9      395083.285
     1653863.913      395152.835     1653764.017      395284.849
     1653735.222      395380.315     1653690.922      395383.637
      1653492.85      395493.773     1653304.662      395572.725
     1653142.972      395600.845     1653011.025      395588.948
     1652837.979      395603.008     1652644.383      395673.849
     1652570.838      395682.501     1652423.208      395810.123
     1652206.901      395830.131     1652103.073      395881.504
     1652032.773      395936.663     1651981.085      396015.006

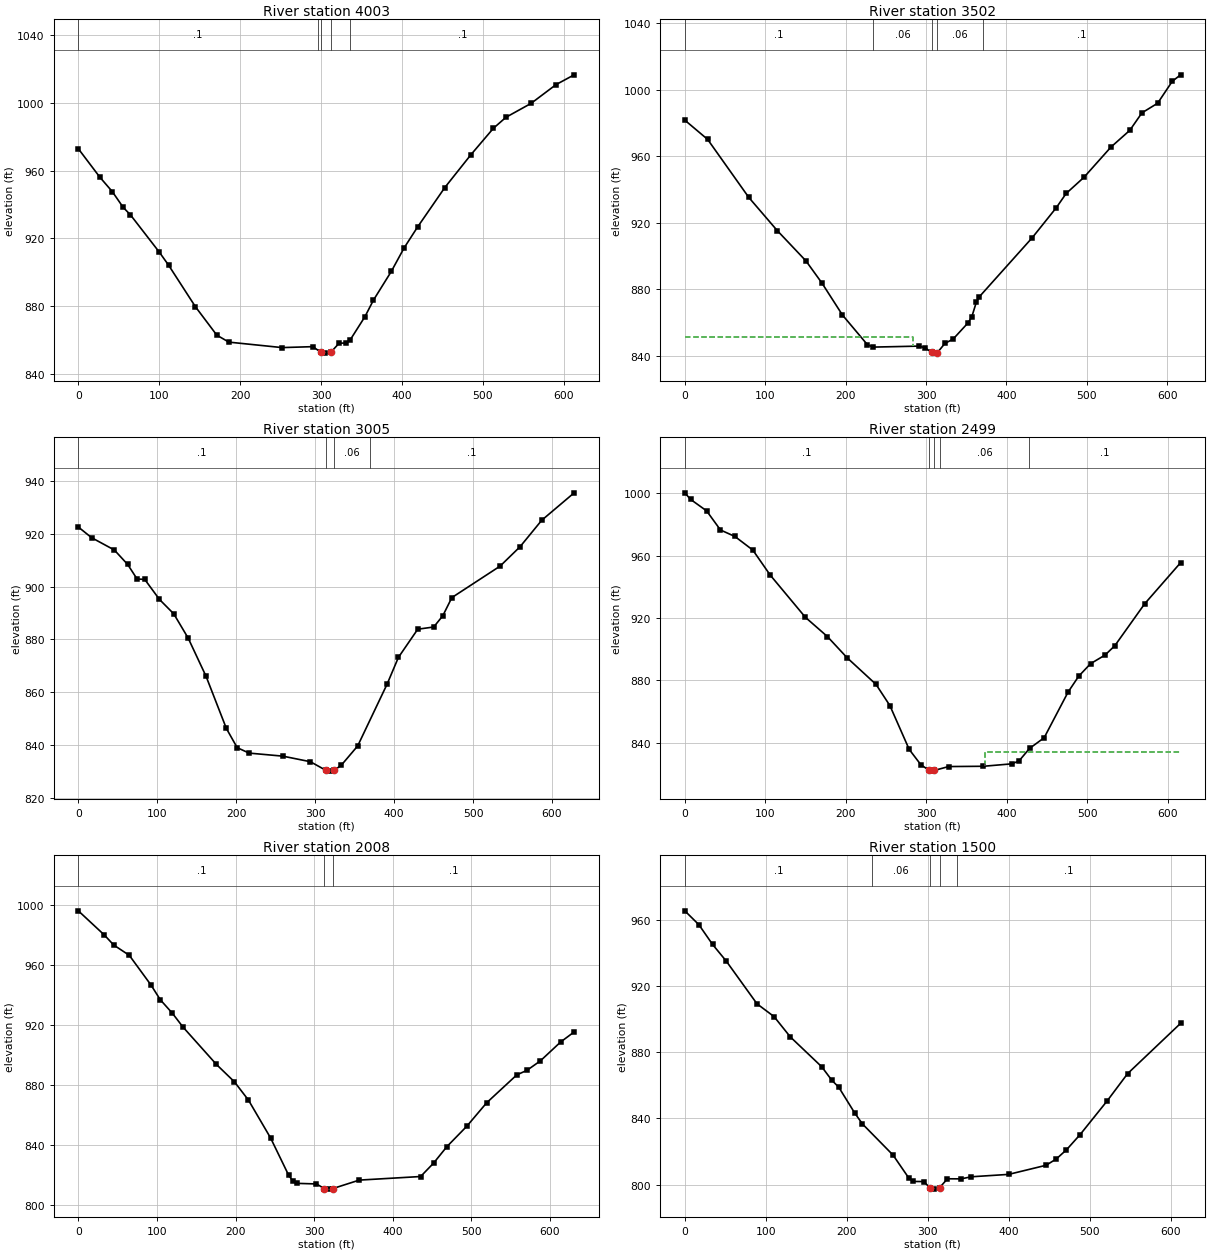
Type RM Length L Ch R = 1 ,4003    ,498,500.5,502.1
XS GIS Cut Line= 6
1654654.46680567393684.6801203341654884.25374767393798.506992429
1654974.97961609393840.5817114261655041.42370893393875.521930262
1655117.18241568393919.5772883451655197.54708435393968.122138754
#Sta/Elev= 30
       0  972.99    26.6  956.19      42  947.66    55.5  938.33    64.4  933.95
   100.1  911.92   111.5  904.27   144.8  879.64   171.2  862.88   186.1  858.76
   251.9  855.53   289.8  856.08   300.2 852.725   304.8  852.26   312.1  852.73
   322.4  858.12   331.2  858.23   336.2  860.14   354.3  873.76   364.9   883.6
   386.9  900.49   402.9  914.52   419.4  926.75   453.1  950.08   485.5  969.55
   513.2  985.09   528.7  991.57   559.7  999.77   590.6 1010.87     613 1016.65
#Mann= 5 ,-1,0
       0      .1       0  296.43     .06       0   300.2    .045       0
   312.1     .06       0  336.43      .1       0
Bank Sta=300.2,312.1
XS Rating Curve= 0 ,0
Exp/Cntr(USF)=0,0
Exp/Cntr=0.3,0.1

Type RM Length L Ch R = 1 ,3502    ,495,497.4,499.1
XS GIS Cut Line= 6
1654382.54805817 393990.206740261654457.05611126394049.688904762
1654525.74987151394106.6399063321654581.49254218394158.090590835
1654650.51569809394230.4496980911654827.92282359394415.290207669
#Sta/Elev= 30
       0  981.67    28.4  970.09    79.6  935.16   114.9  915.26   150.7  896.96
   170.6  883.61   196.1  864.38   227.2   846.5   234.5  845.11   291.4   845.7
     299  844.62  307.21841.8638   310.6  841.48  314.19841.8389   323.4  847.29
   333.8  849.99   352.3  859.73   356.9  863.33   362.7  872.36   365.9  875.19
   432.1  910.95   462.1  929.06   474.2  937.54   496.4  947.28   529.9  965.45
   553.4  975.54   568.5  986.07     588  991.86   606.3  1005.1   616.6 1008.95
#Mann= 5 ,-1,0
       0      .1       0  234.57     .06       0  307.21    .045       0
  314.19     .06       0  370.43      .1       0
#XS Ineff= 2 , 0
          283.32  851.45
Permanent Ineff=
       F       F
Bank Sta=307.21,314.19
XS Rating Curve= 0 ,0
Exp/Cntr(USF)=0,0
Exp/Cntr=0.3,0.1

Type RM Length L Ch R = 1 ,3005    ,508.9,505.9,500.5
XS GIS Cut Line= 6
1654109.62176676394222.5051601681654162.27258009394302.056182176
1654204.26987143394380.0402781671654261.44232926394545.946442425
1654356.90145592394686.3703741731654423.44725458394759.134992421
#Sta/Elev= 30
       0  922.52    16.8  918.49    45.6  913.83    62.5  908.36    74.4  902.86
    84.1   902.7   102.8  895.11   120.9  889.66   139.1   880.5   161.8  866.02
   187.5   846.3   201.2  839.04   216.3  836.98     259  835.83   293.9  833.72
  313.12830.5417   319.6  830.16  324.39830.5253   333.1  832.41   353.8  839.68
   391.1  863.09   405.4  873.19   429.9  883.86   450.1  884.69   461.6  888.93
   473.1  895.82   534.2  907.73   559.4  915.04     587   925.1     628  935.46
#Mann= 4 ,-1,0
       0      .1       0  313.12    .045       0  324.39     .06       0
  369.55      .1       0
Bank Sta=313.12,324.39
XS Rating Curve= 0 ,0
Exp/Cntr(USF)=0,0
Exp/Cntr=0.3,0.1

Type RM Length L Ch R = 1 ,2499    ,491.2,491.3,490.5
XS GIS Cut Line= 6
1653689.92345917394769.6028192491653771.12998967394817.527920261
 1653848.5858715 394858.959267841654011.73154259394922.427316755
1654080.35771768394954.3829615121654243.86296809395036.293886915
#Sta/Elev= 30
       0 1000.42     7.2   996.2    27.1  988.83    44.3  976.57    62.2  972.41
    84.5  963.66   106.1   947.6   149.8  920.48   177.1  908.14   201.5  894.57
   237.5  877.42   254.7  863.83   278.7  835.68   293.3  825.77  303.65822.2206
   306.1  821.74  310.04822.2125   327.6  824.67   370.9  824.86   406.1  826.42
     415  828.24   428.2  836.33   446.3  843.17   476.1  872.57   489.4   882.8
     504  890.74   521.9  896.25     534  902.21   571.2  929.21   615.8  955.58
#Mann= 5 ,-1,0
       0      .1       0  303.65    .045       0  310.04      .1       0
  317.16     .06       0  427.19      .1       0
#XS Ineff= 2 , 0
                           373.4          834.02
Permanent Ineff=
       F       F
Bank Sta=303.65,310.04
XS Rating Curve= 0 ,0
Exp/Cntr(USF)=0,0
Exp/Cntr=0.3,0.1

Type RM Length L Ch R = 1 ,2008    ,500,507.6,510.5
XS GIS Cut Line= 6
1653496.11577593395140.8724179271653567.35874367395208.581272006
1653704.86010909 395311.649307341653801.39272442395341.258828178
1653875.28857401395357.5895041671654048.07661426 395420.18157059
#Sta/Elev= 30
       0  996.42    33.1  980.24      45  973.56    64.8  966.68    92.4  946.83
   104.3  936.94   119.6  927.96     133  918.77   175.7  893.68   198.6  882.05
   216.4  869.85   244.5   844.6   267.4  819.78   273.2  815.49   277.8  814.19
   302.9   813.8   312.9810.7155   318.3  810.33   323.8  810.72   357.3  816.36
   435.4  818.76   451.9  827.73   468.8  838.74   494.1  852.36   519.4  868.07
   557.7  886.71   570.6  889.74   587.7  896.08   613.5  908.71   630.7  915.44
#Mann= 3 ,-1,0
       0      .1       0   312.9    .045       0   323.8      .1       0
Bank Sta=312.9,323.8
XS Rating Curve= 0 ,0
Exp/Cntr(USF)=0,0
Exp/Cntr=0.3,0.1

Type RM Length L Ch R = 1 ,1500    ,498.8,500,501.1
XS GIS Cut Line= 6
1653239.39909776395272.0768799191653269.64247559395360.832936004
1653296.51807801395444.1037668441653319.33988276395515.547193512
1653399.21701959395765.5988587591653427.74484967395854.903142095
#Sta/Elev= 30
       0   965.3    17.4  956.92    34.3  945.02    51.2  934.97    89.2  909.18
   110.3  901.45   130.4  889.19   169.1  871.22   181.7  863.01   190.1  858.91
   209.9  843.28   219.5  836.66   257.3  817.87   276.8  803.99   282.5  801.98
   295.1  801.91  302.75798.2477   307.7  797.35  314.72798.2469   324.5  803.59
   341.3  803.54   353.9   804.8   400.1  806.25   446.3  811.75   458.9  815.55
   471.5  821.08   488.3  830.24   521.9  850.69     547  867.04   612.5  897.42
#Mann= 5 ,-1,0
       0      .1       0  231.27     .06       0  302.75    .045       0
  314.72     .06       0  336.27      .1       0
Bank Sta=302.75,314.72
XS Rating Curve= 0 ,0
Exp/Cntr(USF)=0,0
Exp/Cntr=0.3,0.1

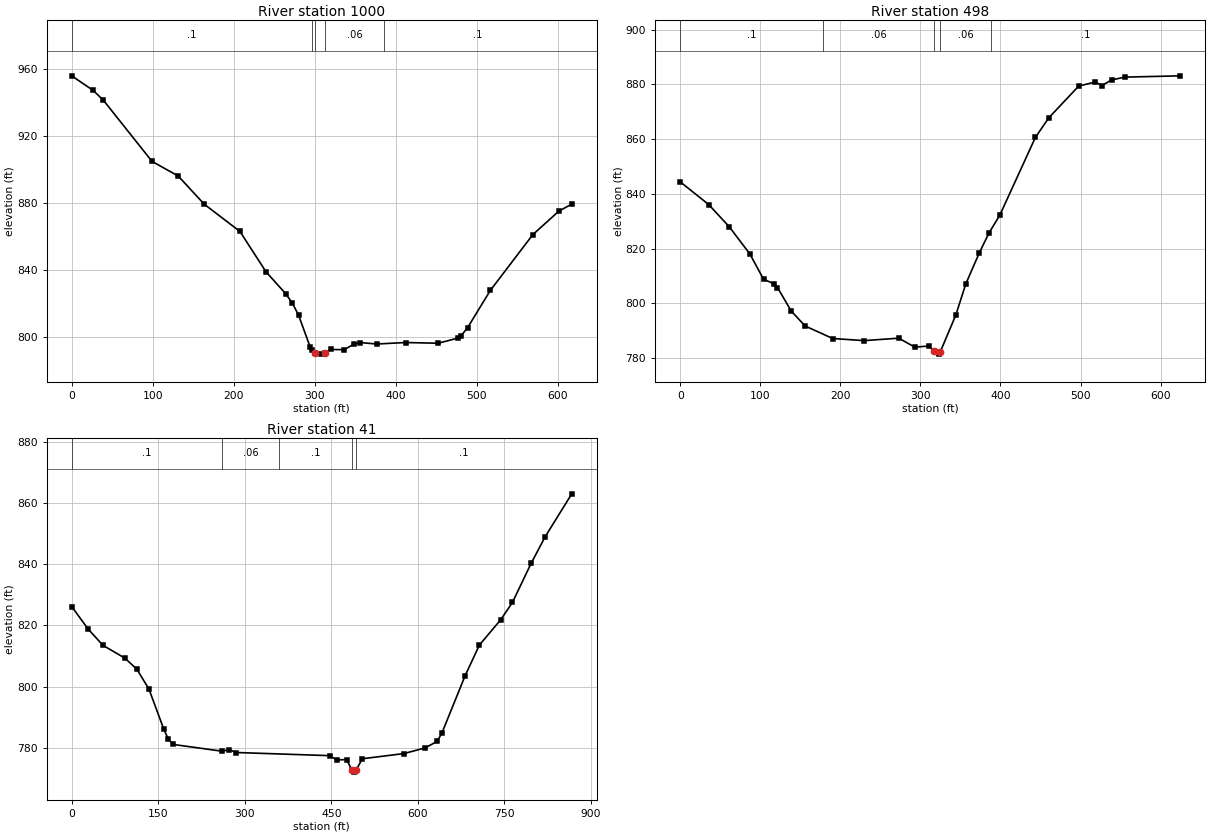
Type RM Length L Ch R = 1 ,1000    ,503.3,501.7,499.9
XS GIS Cut Line= 6
1652814.11025018395297.6499915121652838.17713118395552.767263427
 1652847.6666135395652.3274317531652850.74075434395728.462122008
1652859.40182626 395817.443243251652872.01269342395912.274418429
#Sta/Elev= 30
       0  955.66    26.5     947    39.1  941.17    99.3   904.7   131.5  896.07
   163.6  879.31   207.8  863.04   239.9  839.09   264.1  826.09   272.5  820.41
   280.1  813.32   294.5  794.25   296.2  792.43   300.2  790.69   308.3  790.06
   312.3  790.71   320.3  792.84   336.4  792.67   348.4     796   356.5  796.93
   376.5  796.08   412.5  796.96   452.6  796.54   476.7  799.57   480.8  800.99
   488.8  805.74   516.9  827.94   569.4  861.16   601.6  875.16   617.5  879.32
#Mann= 5 ,-1,0
       0      .1       0  296.25     .06       0   300.2    .045       0
   312.3     .06       0  386.26      .1       0
Bank Sta=300.2,312.3
XS Rating Curve= 0 ,0
Exp/Cntr(USF)=0,0
Exp/Cntr=0.3,0.1

Type RM Length L Ch R = 1 ,498     ,460.9,457.5,455.4
XS GIS Cut Line= 6
1652288.82980467395519.5622773321652324.52691175395611.155926168
1652358.99108167395696.1918453431652389.68721451395768.188420504
1652419.14483276395863.9913785011652486.57120709396111.211356506
#Sta/Elev= 30
       0  844.39    35.4  836.13    61.1  828.01    86.9  818.06   104.1  808.76
   117.1  807.18   121.4   805.8   138.6  797.19   155.9  791.74   190.4  787.16
   229.6  786.39   272.9  787.28     293     784   310.5  784.41  317.45782.4225
   323.1  781.45  324.91 782.374   344.2  795.72   356.6  807.07   373.3  818.29
   385.7  825.77   399.1  832.19   443.6  860.64   460.3  867.79   497.7  879.41
   518.4   880.9   526.7  879.62   539.1  881.68   555.5  882.69   624.8  883.16
#Mann= 5 ,-1,0
       0      .1       0   178.3     .06       0  317.45    .045       0
  324.91     .06       0  388.56      .1       0
Bank Sta=317.45,324.91
XS Rating Curve= 0 ,0
Exp/Cntr(USF)=0,0
Exp/Cntr=0.3,0.1

Type RM Length L Ch R = 1 ,41      ,,,
XS GIS Cut Line= 4
 1652093.5861225395537.3614078961651955.27892618395953.990493088
1652035.53124997395998.3853956081652365.07802637396064.977749389
#Sta/Elev= 30
       0  826.16    28.6  818.79    54.3  813.47    91.9  809.33   112.9  805.71
     134  799.16   159.3  786.27   167.7  782.73   176.1  781.09   260.4   778.9
   273.1  779.37   285.7  778.46   447.4  777.43   459.1  776.05   476.8  776.13
   485.8  772.72   490.2  772.05  492.98772.7104   503.9  776.42   576.2  778.12
   612.9  779.99   633.3  782.06   641.5  784.69   682.1  803.58   706.8  813.58
   743.5  821.78     764  827.48   796.5  840.29     821  849.03   866.9  862.98
#Mann= 5 ,-1,0
       0      .1       0     260     .06       0     360      .1       0
   485.8    .045       0  492.98      .1       0
Bank Sta=485.8,492.98
XS Rating Curve= 0 ,0
Exp/Cntr(USF)=0,0
Exp/Cntr=0.3,0.1
LCMann Table=0

Chan Stop Cuts=-1
Use User Specified Reach Order=0
Composite Channel Slope=5