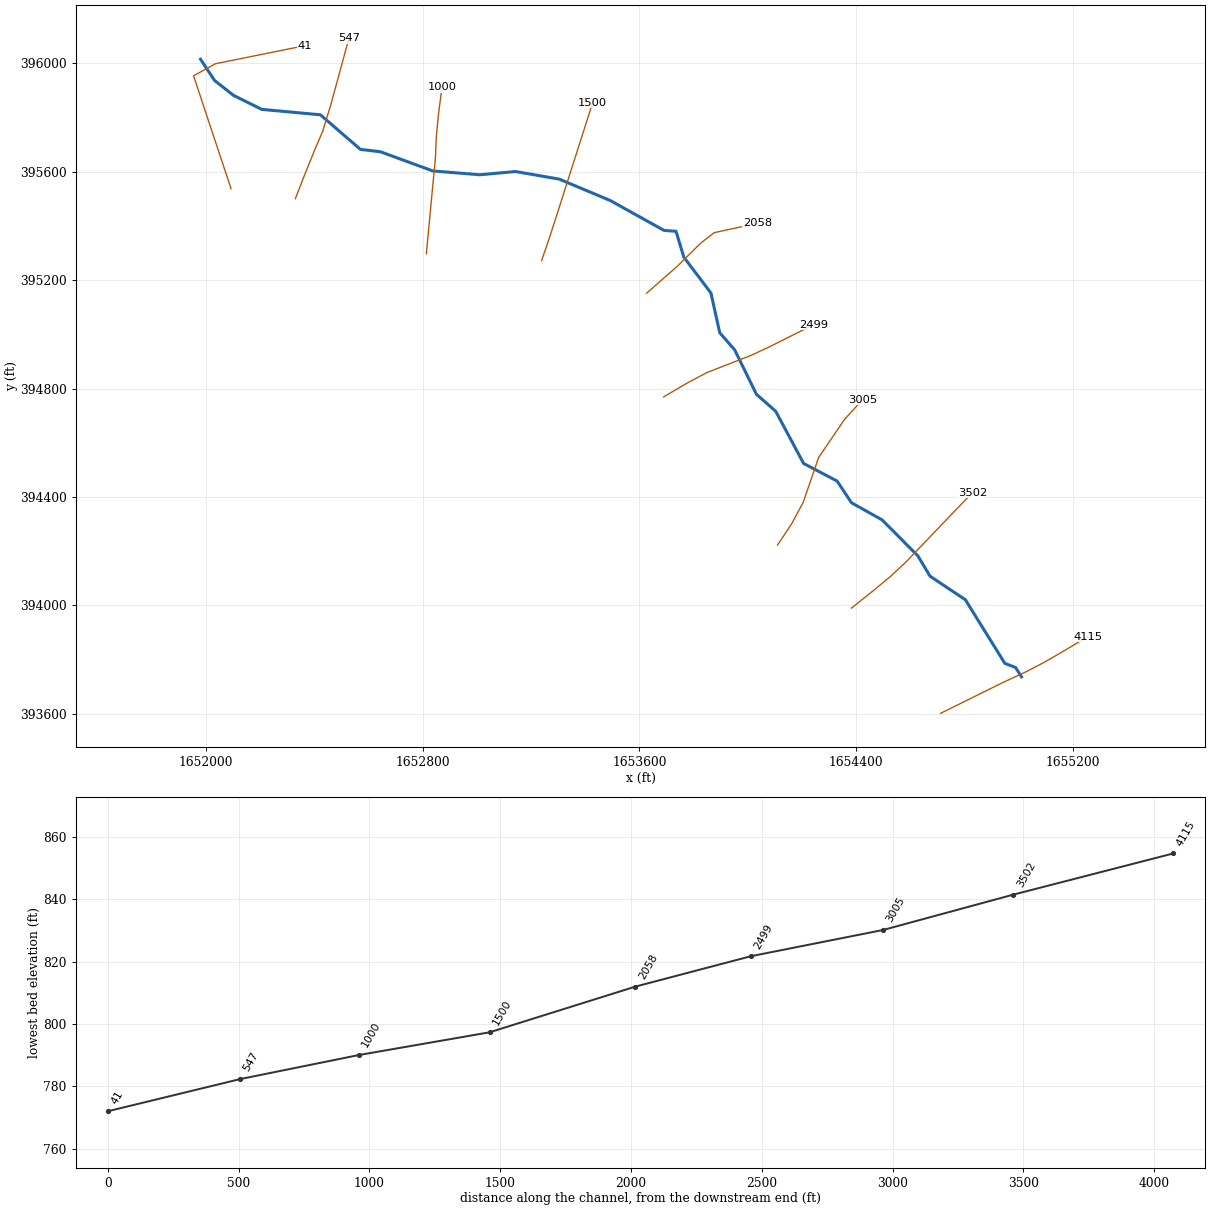
--- SHEEPRN.prj (project) ---

Proj Title=SHEEPRN
Current Plan=p01
Default Exp/Contr=0,0
English Units
Geom File=g01
Flow File=f01
Plan File=p01
BEGIN DESCRIPTION:
---------- MODELED AS PART OF WVEMD CTP PROGRAM, 2023----------
Stream Name: Sheep Run
Flood Zone:  AFH
Wetzel County, WV
HEC-RAS Version: RAS 6.3
Vertical Datum: NAVD88
Projection: NAD 1983 StatePlane West Virginia S FIPS 4702 (US Feet)
Terrain: 1-meter West Virginia FEMA R3 South Central (collected 2018-2020)
Land Use: 2019 NLCD
Hydrologic Method:
WV SIR2010-5033 regression equations
Additional Model Notes:
None
END DESCRIPTION:
DSS Export Rating Curves= 0
DSS Export Rating Curve Sorted= 0
DSS Export Volume Flow Curves= 0
DXF OffsetX= 0
DXF OffsetY= 0
DXF ScaleX= 0
DXF ScaleY= 0

--- SHEEPRN.p01 (plan) ---

Plan Title=Floodplain
Program Version=6.30
Short Identifier=Floodplain
Geom File=g01
Flow File=f01
Subcritical Flow
K Sum by GR= 0
Std Step Tol= 0.01
Critical Tol= 0.01
Num of Std Step Trials= 20
Max Error Tol= 0.3
Flow Tol Ratio= 0.001
Split Flow NTrial= 30
Split Flow Tol= 0.02
Split Flow Ratio= 0.02
Log Output Level= 0
Friction Slope Method= 1
Unsteady Friction Slope Method= 2
Unsteady Bridges Friction Slope Method= 1
Parabolic Critical Depth
Global Vel Dist= 0 , 0 , 0
Global Log Level= 0
CheckData=False
Encroach Param=-1 ,0,0, 0
Mapping Interval=1HOUR
Computation Time Step Use Courant=        0
Computation Time Step Use Time Series=    0
Computation Time Step Count To Double=0
Computation Time Step Max Doubling=0
Computation Time Step Max Halving=0
Computation Time Step Residence Courant=0
Run HTab= 0
Run UNet= 0
Run Sediment= 0
Run PostProcess= 0
Run WQNet= 0
Run RASMapper=-1
UNET Theta= 0
UNET Theta Warmup= 0
UNET ZTol= 0
UNET ZSATol= 0
UNET MxIter= 0
UNET Max Iter WO Improvement= 0
UNET MaxInSteps= 0
UNET DtIC= 0
UNET DtMin= 0
UNET MaxCRTS= 0
UNET WFStab= 0
UNET SFStab= 0
UNET WFX= 1
UNET SFX= 1
UNET Gravity=32.17405
UNET 1D Methodology=Finite Difference
UNET DSS MLevel= 1
UNET Pardiso=0
UNET DZMax Abort= 0
UNET Use Existing IB Tables= 0
UNET Froude Reduction=False
UNET Froude Limit= 0
UNET Froude Power= 0
UNET D1 Cores= 0
UNET WindReference=Eulerian
UNET WindDragFormulation=Hsu (1988)
UNET D2 Coriolis=0
UNET D2 Cores= 0
UNET D2 Theta= 1
UNET D2 Theta Warmup= 1
UNET D2 Z Tol= 0.01
UNET D2 Volume Tol= 0.01
UNET D2 Max Iterations= 20
UNET D2 Equation= 0
UNET D2 RampUpFraction=0.1
UNET D2 TimeSlices= 1
UNET D2 Turbulence Formulation=Non-Conservative (original)
UNET D2 Eddy Viscosity=0.3
UNET D2 Transverse Eddy Viscosity=0.1
UNET D2 Smagorinsky Mixing=0
UNET D2 BCVolumeCheck=0
UNET D2 Cores=0
UNET D2 SolverType=PARDISO (Direct)
UNET D2 Minimum Iterations= 3
UNET D2 Maximum Iterations= 30
UNET D2 Restart Number= 10
UNET D2 Relaxation Coeff=1.3
UNET D2 SOR Precondition Iterations= 10
UNET D2 ILUT Maximum Fill= 8
UNET D2 ILUT Tolerance=1E-08
UNET D2 Convergence Tolerance=0.00001
UNET D1D2 MaxIter= 0
UNET D1D2 ZTol=0.01
UNET D1D2 QTol=0.1
UNET D1D2 MinQTol=1
Write IC File= 0
Write IC File at Fixed DateTime=0
Write IC File at Sim End=0
Echo Input=False
Echo Parameters=False
Echo Output=False
Write Detailed= 0
HDF Write Warmup=0
HDF Write Time Slices=0
HDF Flush=0
HDF Compression= 1
HDF Chunk Size= 1
HDF Spatial Parts= 1
HDF Use Max Rows=0
HDF Fixed Rows= 1
Calibration Method= 0
Calibration Iterations= 20
Calibration Max Change=0.05
Calibration Tolerance=0.2
Calibration Maximum=1.5
Calibration Minimum=0.5
Calibration Optimization Method= 1
WQ AD Non Conservative
WQ ULTIMATE=-1
WQ Max Comp Step=1HOUR
WQ Output Interval=15MIN
WQ Output Selected Increments= 0
WQ Output face flow=0
WQ Output face velocity=0
WQ Output face area=0
WQ Output face dispersion=0
WQ Output cell volume=0
WQ Output cell surface area=0
WQ Output cell continuity=0
WQ Output cumulative cell continuity=0
WQ Output face conc=0
WQ Output face dconc_dx=0
WQ Output face courant=0
WQ Output face peclet=0
WQ Output face adv mass=0
WQ Output face disp mass=0
WQ Output cell mass=0
WQ Output cell source sink temp=0
WQ Output nsm pathways=0
WQ Output nsm derived pathways=0
WQ Create Restart=0
WQ Fixed Restart=0
WQ System Summary=0
WQ Write To DSS=0
Sorting and Armoring Iterations= 10
XS Update Threshold= 0.02
Bed Roughness Predictor= 0
Hydraulics Update Threshold= 0.02
Energy Slope Method= 1
Volume Change Method= 1
Sediment Retention Method= 0
Sediment TS Multiplier= 1
Warm Up Method= 0
XS Weighting Method= 0
Number of US Weighted Cross Sections= 1
Number of DS Weighted Cross Sections= 1
Upstream XS Weight=0
Main XS Weight=1
Downstream XS Weight=0
Number of DS XS's Weighted with US Boundary= 1
Upstream Boundary Weight= 1
Weight of XSs Associated with US Boundary= 0
Number of US XS's Weighted with DS Boundary= 1
Downstream Boundary Weight= 0.5
Weight of XSs Associated with DS Boundary= 0.5
Percentile Method= 0
Sediment Output Level= 3
Mass or Volume Output= 0
Output Increment Type= 1
Profile and TS Output Increment= 1
Transport Output Increment 1
XS Output Flag= 0
XS Output Increment= 10
Read HDF5 Sediment Hotstart= 0
Sediment Hotstart Type= 0
Write Gradation File= 0
Read Gradation Hotstart= 0
Write HDF5 File= 1
Write Binary Output= 1
Write DSS Sediment File= 0
DSS Sediment Output Type= 1
SV Curve= 0
Specific Gage Flag= 0
Subcell Erosion Methods= 0
Subcell Deposition Methods= 0
Advection Scheme= 1
Matrix Solver= 0
Implicit Weighting Factor= 1
Maximum Outer Loop Convergence Iterations= 5
Convergence Maximum Absolute= 0.001
Convergence RMSE= 0.0001
Grain Fractions Max Abs Error= 0.001
Max Subgrid Regions= 1
Max Subgrid Length Scale= 3.402823E+38
Initial Layer Thickness= 3.402823E+38
Min Layer Thickness= 3.402823E+38
Max Layer Thickness= 3.402823E+38
Number of Layers= 5

--- SHEEPRN.f01 (steady flow) ---

Flow Title=Flow
Program Version=6.30
Number of Profiles= 1
Profile Names=F01pct
River Rch & RM=SHEEPRN,Main,4115
     579
River Rch & RM=SHEEPRN,Main,2499
     670
Boundary for River Rch & Prof#=SHEEPRN,Main            , 1
Up Type= 0
Dn Type= 3
Dn Slope=0.01867
DSS Import GetInterval= 0
DSS Import GetPeak= 0
DSS Import FillOption= 0

--- SHEEPRN.g01 (geometry) ---

Geom Title=Geometry
Program Version=6.30

River Reach=SHEEPRN         ,Main
Reach XY= 30
1655009.82641302393736.3876762421654988.01902202393770.970261497
1654948.41822021393786.264440426     1654802.723      394020.934
     1654672.163      394108.246      1654627.42      394182.891
     1654495.407       394315.79     1654382.664      394378.696
     1654329.504      394458.879     1654205.908      394523.778
      1654102.91      394716.482     1654031.809      394779.166
     1653951.627      394942.854     1653896.473      395006.203
     1653863.913      395152.835     1653764.017      395284.849
     1653735.222      395380.315     1653690.922      395383.637
      1653492.85      395493.773     1653304.662      395572.725
     1653142.972      395600.845     1653011.025      395588.948
     1652837.979      395603.008     1652644.383      395673.849
     1652570.838      395682.501     1652423.208      395810.123
     1652206.901      395830.131     1652103.073      395881.504
     1652032.773      395936.6631651981.08480129396015.005868927

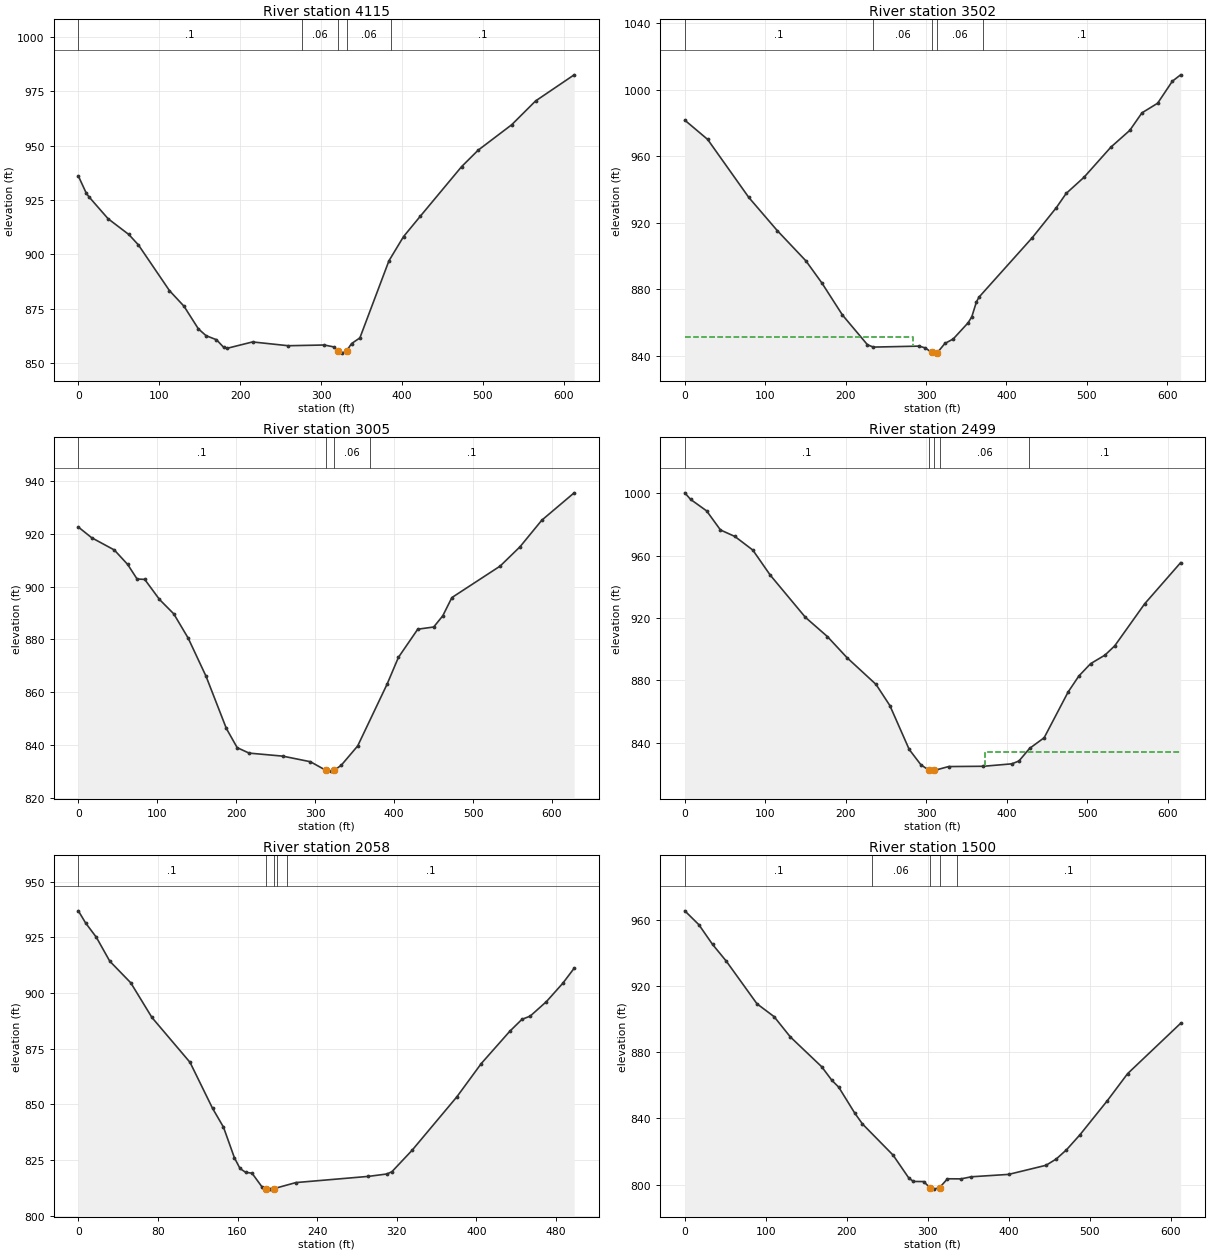
Type RM Length L Ch R = 1 ,4115    ,610.1,612.4,613.5
XS GIS Cut Line= 6
1654711.17279571 393601.802134891654940.95973771393715.629006985
1655031.68560613393757.7037259821655098.12969897393792.643944818
1655173.88840572393836.6993029011655254.25307439 393885.24415331
#Sta/Elev= 30
       0  936.06      10  928.01    13.8   926.2    36.8  916.42    62.4  909.19
    74.3  904.39   112.7  883.39   130.6  876.26   148.4  865.86   157.9  862.72
   170.8  860.85   179.7  857.36   184.2  856.94   215.4  859.84   259.5   858.1
     304  858.43   315.6  857.57   321.6  855.68   326.1   854.7  331.57   855.7
   337.8  859.09   348.1   861.7     384   897.1   402.1  908.24   422.7  917.53
   473.8  940.33   494.3   947.9   535.8  959.59   565.3  970.51     613  982.51
#Mann= 5 ,-1,0
       0      .1       0  276.43     .06       0   321.6    .045       0
  331.57     .06       0  386.44      .1       0
Bank Sta=321.6,331.57
XS Rating Curve= 0 ,0
Exp/Cntr(USF)=0,0
Exp/Cntr=0.3,0.1

Type RM Length L Ch R = 1 ,3502    ,494.9,497.4,499.1
XS GIS Cut Line= 6
1654382.54805817 393990.206740261654457.05611126394049.688904762
1654525.74987151394106.6399063321654581.49254218394158.090590835
1654650.51569809394230.4496980911654827.92282359394415.290207669
#Sta/Elev= 30
       0  981.67    28.4  970.09    79.6  935.16   114.9  915.26   150.7  896.96
   170.6  883.61   196.1  864.38   227.2   846.5   234.5  845.11   291.4   845.7
     299  844.62   307.2 841.866   310.6  841.48   314.2841.8416   323.4  847.29
   333.8  849.99   352.3  859.73   356.9  863.33   362.7  872.36   365.9  875.19
   432.1  910.95   462.1  929.06   474.2  937.54   496.4  947.28   529.9  965.45
   553.4  975.54   568.5  986.07     588  991.86   606.3  1005.1   616.6 1008.95
#Mann= 5 ,-1,0
       0      .1       0  234.57     .06       0   307.2    .045       0
   314.2     .06       0  370.43      .1       0
#XS Ineff= 2 , 0
          283.32  851.45
Permanent Ineff=
       F       F
Bank Sta=307.2,314.2
XS Rating Curve= 0 ,0
Exp/Cntr(USF)=0,0
Exp/Cntr=0.3,0.1

Type RM Length L Ch R = 1 ,3005    ,508.9,505.9,500.5
XS GIS Cut Line= 6
1654109.62176676394222.5051601681654162.27258009394302.056182176
1654204.26987143394380.0402781671654261.44232926394545.946442425
1654356.90145592394686.3703741731654423.44725458394759.134992421
#Sta/Elev= 30
       0  922.52    16.8  918.49    45.6  913.83    62.5  908.36    74.4  902.86
    84.1   902.7   102.8  895.11   120.9  889.66   139.1   880.5   161.8  866.02
   187.5   846.3   201.2  839.04   216.3  836.98     259  835.83   293.9  833.72
   313.1830.5443   319.6  830.16   324.4830.5269   333.1  832.41   353.8  839.68
   391.1  863.09   405.4  873.19   429.9  883.86   450.1  884.69   461.6  888.93
   473.1  895.82   534.2  907.73   559.4  915.04     587   925.1     628  935.46
#Mann= 4 ,-1,0
       0      .1       0   313.1    .045       0   324.4     .06       0
  369.55      .1       0
Bank Sta=313.1,324.4
XS Rating Curve= 0 ,0
Exp/Cntr(USF)=0,0
Exp/Cntr=0.3,0.1

Type RM Length L Ch R = 1 ,2499    ,439.7,441.1,442.5
XS GIS Cut Line= 6
1653689.92345917394769.6028192491653771.12998967394817.527920261
 1653848.5858715 394858.959267841654011.73154259394922.427316755
1654080.35771768394954.3829615121654243.86296809395036.293886915
#Sta/Elev= 30
       0 1000.42     7.2   996.2    27.1  988.83    44.3  976.57    62.2  972.41
    84.5  963.66   106.1   947.6   149.8  920.48   177.1  908.14   201.5  894.57
   237.5  877.42   254.7  863.83   278.7  835.68   293.3  825.77   303.6822.2304
   306.1  821.74     310 822.205   327.6  824.67   370.9  824.86   406.1  826.42
     415  828.24   428.2  836.33   446.3  843.17   476.1  872.57   489.4   882.8
     504  890.74   521.9  896.25     534  902.21   571.2  929.21   615.8  955.58
#Mann= 5 ,-1,0
       0      .1       0   303.6    .045       0     310      .1       0
  317.16     .06       0  427.19      .1       0
#XS Ineff= 2 , 0
                           373.4          834.02
Permanent Ineff=
       F       F
Bank Sta=303.6,310
XS Rating Curve= 0 ,0
Exp/Cntr(USF)=0,0
Exp/Cntr=0.3,0.1

Type RM Length L Ch R = 1 ,2058    ,556.1,557.8,559.7
XS GIS Cut Line= 5
1653626.55045802395151.6618230321653739.28456583395250.797994925
1653827.47185831395337.7816103261653876.08190216395375.321434404
1654035.40848812395409.817966078
#Sta/Elev= 30
       0  936.91     7.4  931.41    18.1  925.05    31.6  914.31    52.7  904.61
      74  889.04   112.3  868.89   134.9  848.29   145.9  839.83   156.9  826.07
   162.5  821.28   168.1  819.57   174.6  819.16     185  812.78   188.7  812.18
   192.5  812.01   196.2  812.18   218.7  814.95   291.6  817.73   310.2  818.81
   315.2  819.83   335.4   829.4   380.5  853.44     405  868.36   433.7  882.86
   445.9   888.2   454.2  889.66   470.5  896.16   486.9  904.36   498.4  911.15
#Mann= 5 ,-1,0
       0      .1       0   188.7    .045       0   196.2      .1       0
  200.12     .06       0  210.12      .1       0
Bank Sta=188.7,196.2
XS Rating Curve= 0 ,0
Exp/Cntr(USF)=0,0
Exp/Cntr=0.3,0.1

Type RM Length L Ch R = 1 ,1500    ,498.9,500,501.1
XS GIS Cut Line= 6
1653239.39909776395272.0768799191653269.64247559395360.832936004
1653296.51807801395444.1037668441653319.33988276395515.547193512
1653399.21701959395765.5988587591653427.74484967395854.903142095
#Sta/Elev= 30
       0   965.3    17.4  956.92    34.3  945.02    51.2  934.97    89.2  909.18
   110.3  901.45   130.4  889.19   169.1  871.22   181.7  863.01   190.1  858.91
   209.9  843.28   219.5  836.66   257.3  817.87   276.8  803.99   282.5  801.98
   295.1  801.91   302.8798.2239   307.7  797.35   314.7798.2431   324.5  803.59
   341.3  803.54   353.9   804.8   400.1  806.25   446.3  811.75   458.9  815.55
   471.5  821.08   488.3  830.24   521.9  850.69     547  867.04   612.5  897.42
#Mann= 5 ,-1,0
       0      .1       0  231.27     .06       0   302.8    .045       0
   314.7     .06       0  336.27      .1       0
Bank Sta=302.8,314.7
XS Rating Curve= 0 ,0
Exp/Cntr(USF)=0,0
Exp/Cntr=0.3,0.1

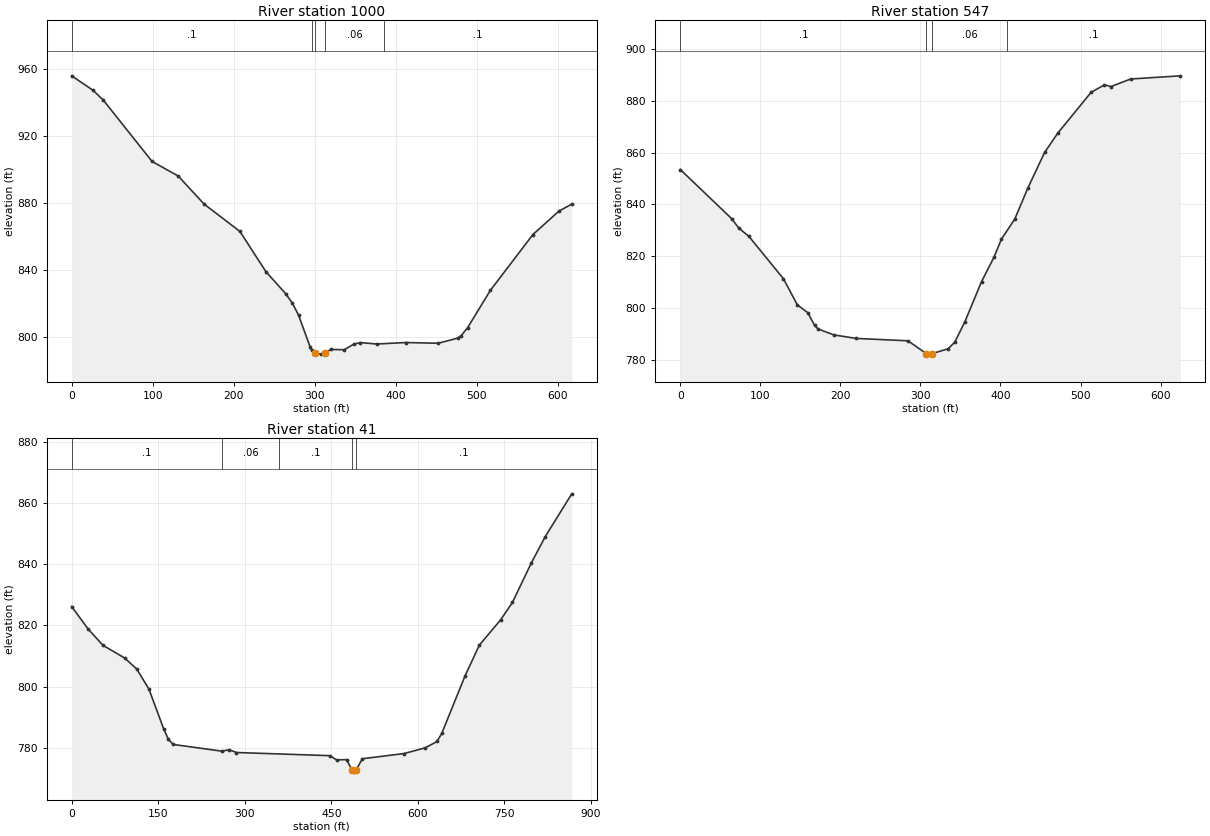
Type RM Length L Ch R = 1 ,1000    ,454.2,453.3,451.5
XS GIS Cut Line= 6
1652814.11025018395297.6499915121652838.17713118395552.767263427
 1652847.6666135395652.3274317531652850.74075434395728.462122008
1652859.40182626 395817.443243251652872.01269342395912.274418429
#Sta/Elev= 30
       0  955.66    26.5     947    39.1  941.17    99.3   904.7   131.5  896.07
   163.6  879.31   207.8  863.04   239.9  839.09   264.1  826.09   272.5  820.41
   280.1  813.32   294.5  794.25   296.2  792.43   300.2  790.69   308.3  790.06
   312.3  790.71   320.3  792.84   336.4  792.67   348.4     796   356.5  796.93
   376.5  796.08   412.5  796.96   452.6  796.54   476.7  799.57   480.8  800.99
   488.8  805.74   516.9  827.94   569.4  861.16   601.6  875.16   617.5  879.32
#Mann= 5 ,-1,0
       0      .1       0  296.25     .06       0   300.2    .045       0
   312.3     .06       0  386.26      .1       0
Bank Sta=300.2,312.3
XS Rating Curve= 0 ,0
Exp/Cntr(USF)=0,0
Exp/Cntr=0.3,0.1

Type RM Length L Ch R = 1 ,547     ,509.4,505.8,503.8
XS GIS Cut Line= 6
1652330.70499732395500.587580664 1652366.4021044  395592.1812295
1652400.86627432395677.2171486751652431.56240716395749.213723836
1652461.02002541395845.0166818331652528.44639974396092.236659838
#Sta/Elev= 30
       0  853.46    64.3   834.5    72.9  830.95    85.8  827.68   128.9  811.38
   146.2  801.34   159.1  798.37   167.7   793.5   172.1  792.05     192  789.75
   219.8  788.41   284.4  787.49  307.23  782.58     311  782.36   314.8  782.58
   334.6  784.42   342.9  786.97   355.5  794.82   376.4  810.33     392  819.77
   401.2  826.66   417.8  834.35   434.4  846.45   455.1  860.03   471.7  867.53
   513.2   883.2   529.8  886.07     538  885.44   562.7  888.34   624.8  889.56
#Mann= 4 ,-1,0
       0      .1       0  307.23    .045       0   314.8     .06       0
  408.56      .1       0
Bank Sta=307.23,314.8
XS Rating Curve= 0 ,0
Exp/Cntr(USF)=0,0
Exp/Cntr=0.3,0.1

Type RM Length L Ch R = 1 ,41      ,,,
XS GIS Cut Line= 4
 1652093.5861225395537.3614078961651955.27892618395953.990493088
1652035.53124997395998.3853956081652365.07802637396064.977749389
#Sta/Elev= 30
       0  826.16    28.6  818.79    54.3  813.47    91.9  809.33   112.9  805.71
     134  799.16   159.3  786.27   167.7  782.73   176.1  781.09   260.4   778.9
   273.1  779.37   285.7  778.46   447.4  777.43   459.1  776.05   476.8  776.13
   485.8  772.72   490.2  772.05     493772.7166   503.9  776.42   576.2  778.12
   612.9  779.99   633.3  782.06   641.5  784.69   682.1  803.58   706.8  813.58
   743.5  821.78     764  827.48   796.5  840.29     821  849.03   866.9  862.98
#Mann= 5 ,-1,0
       0      .1       0     260     .06       0     360      .1       0
   485.8    .045       0     493      .1       0
Bank Sta=485.8,493
XS Rating Curve= 0 ,0
Exp/Cntr(USF)=0,0
Exp/Cntr=0.3,0.1
LCMann Table=0

Chan Stop Cuts=-1
Use User Specified Reach Order=0
Composite Channel Slope=5